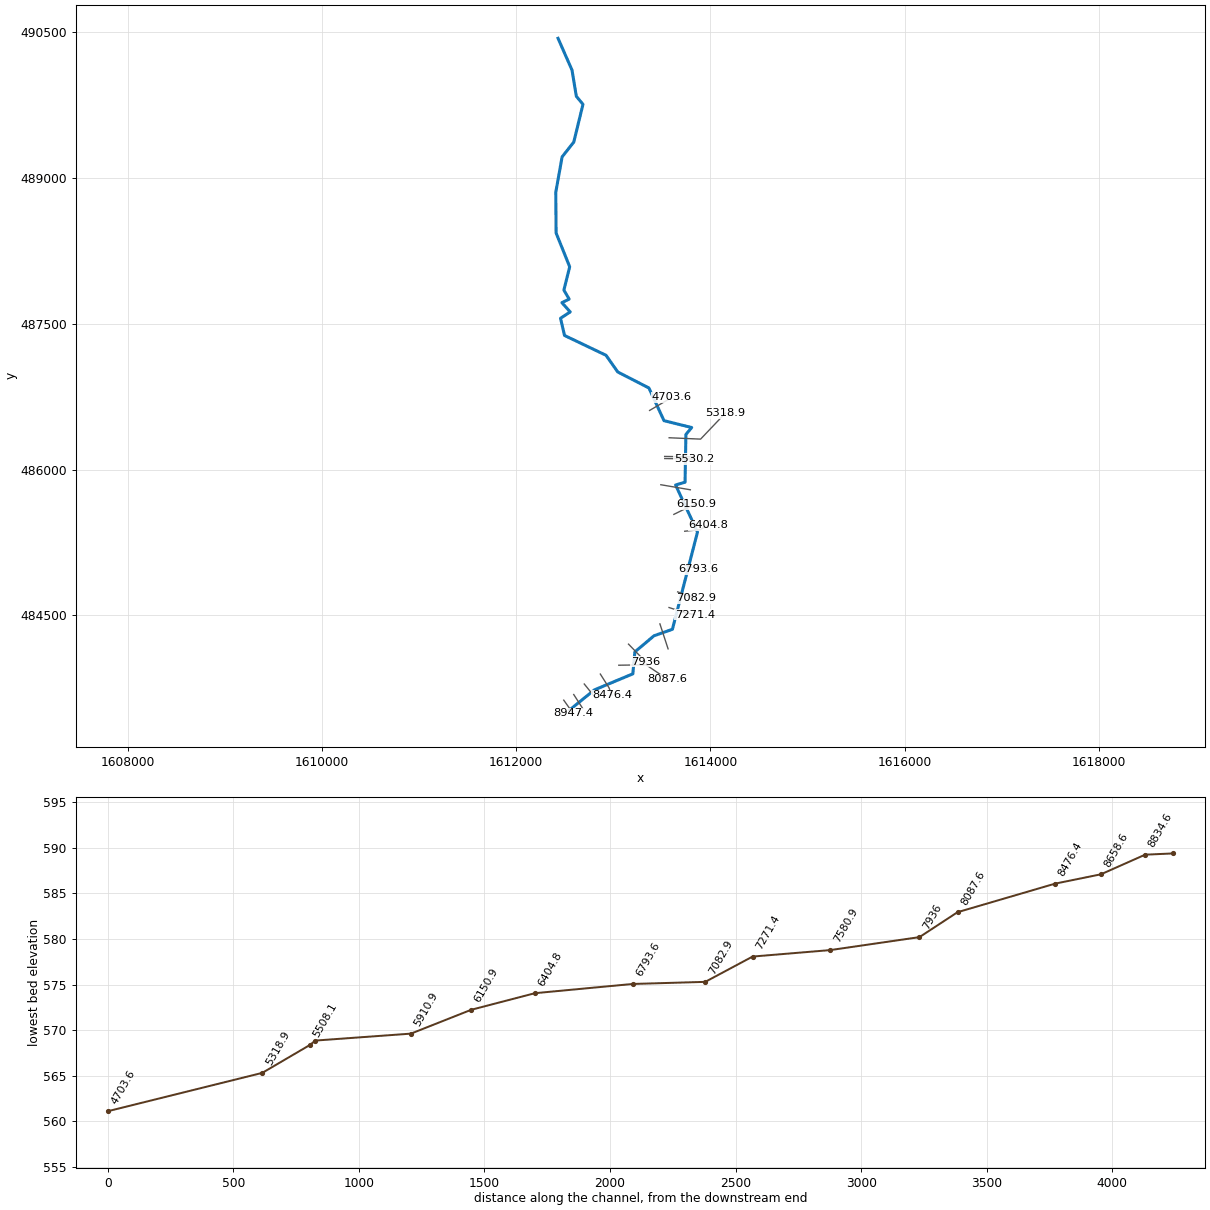
--- SmithCk.prj (project) ---

Proj Title=SmithCk
Current Plan=p01
Geom File=g01
Flow File=f01
Plan File=p01
DSS Export Rating Curves=0
DSS Export Rating Curve Sorted=0
DSS Export Volume Flow Curves=0
DXF OffsetX=0
DXF OffsetY=0
DXF ScaleX=0
DXF ScaleY=0

--- SmithCk.p01 (plan) ---

Plan Title=Floodplain
Program Version=4.00
Geom File=g01
Flow File=f01
K Sum by GR=0
Std Step Tol=0.01
Critical Tol=0.01
Num of Std Step Trials=20
Max Error Tol=0.3
Flow Tol Ratio=0.001
Split Flow NTrial=30
Split Flow Tol=0.02
Split Flow Ratio=0.02
Log Output Level=0
Friction Slope Method=1
Unsteady Friction Slope Method=2
Unsteady Bridges Friction Slope Method=1
Global Log Level=0
CheckData=False
Run HTab=0
Run UNet=0
Run PostProcess=0
UNET Theta=0
UNET Theta Warmup=0
UNET ZTol=0
UNET ZSATol=0
UNET MxIter=0
UNET MaxInSteps=0
UNET DtIC=0
UNET DtMin=0
UNET MaxCRTS=0
UNET WFStab=0
UNET SFStab=0
UNET WFX=0
UNET SFX=0
UNET DSS MLevel=0
UNET DZMax Abort=0
UNET Convert EG Bridges=0
UNET Use Existing IB Tables=0
UNET Froude Limit=0
UNET Froude Power=0
Write IC File=0
Echo Input=False
Echo Output=False
Write Detailed=0

--- SmithCk.f01 (steady flow) ---

Flow Title=NFF Regression Equation
Program Version=4.10
Number of Profiles= 1
Profile Names=P100yr
River Rch & RM=SmithCk,Main            ,8947.4
     888
River Rch & RM=SmithCk,Main            ,8087.6
     902
River Rch & RM=SmithCk,Main            ,7580.9
     936
River Rch & RM=SmithCk,Main            ,7082.9
     944
River Rch & RM=SmithCk,Main            ,6793.6
     947
River Rch & RM=SmithCk,Main            ,6150.9
     976
River Rch & RM=SmithCk,Main            ,5530.2
    1000
River Rch & RM=SmithCk,Main            ,5318.9
    1002
Boundary for River Rch & Prof#=SmithCk,Main            , 1
Up Type= 0
Dn Type= 3
Dn Slope=0.00669
DSS Import GetInterval= 0
DSS Import GetPeak= 0
DSS Import FillOption= 0

--- SmithCk.g01 (geometry) ---

Geom Title=USGS 10m DEM
Program Version=4.10

River Reach=SmithCk         ,Main
Reach XY= 30
      1612551.35      483529.219     1612804.984       483734.16
     1613200.817       483899.09     1613221.651      484124.785
     1613418.854      484290.789     1613608.442      484357.568
     1613866.688      485358.003     1613640.994      485841.943
      1613738.65       485871.24     1613747.331      486361.692
     1613807.009      486433.306     1613521.636      486503.836
     1613366.471      486840.207     1613045.291      487005.138
     1612924.848      487176.579     1612497.331      487380.572
     1612456.098      487557.438     1612555.924      487622.542
     1612470.204      487718.029     1612545.074      487754.921
      1612490.82      487847.152     1612550.499      488086.952
     1612410.525      488435.259      1612407.27      488853.011
     1612472.374      489217.595     1612592.817      489370.589
     1612687.218      489757.959     1612618.858      489841.509
      1612574.37      490110.607     1612430.711      490437.525

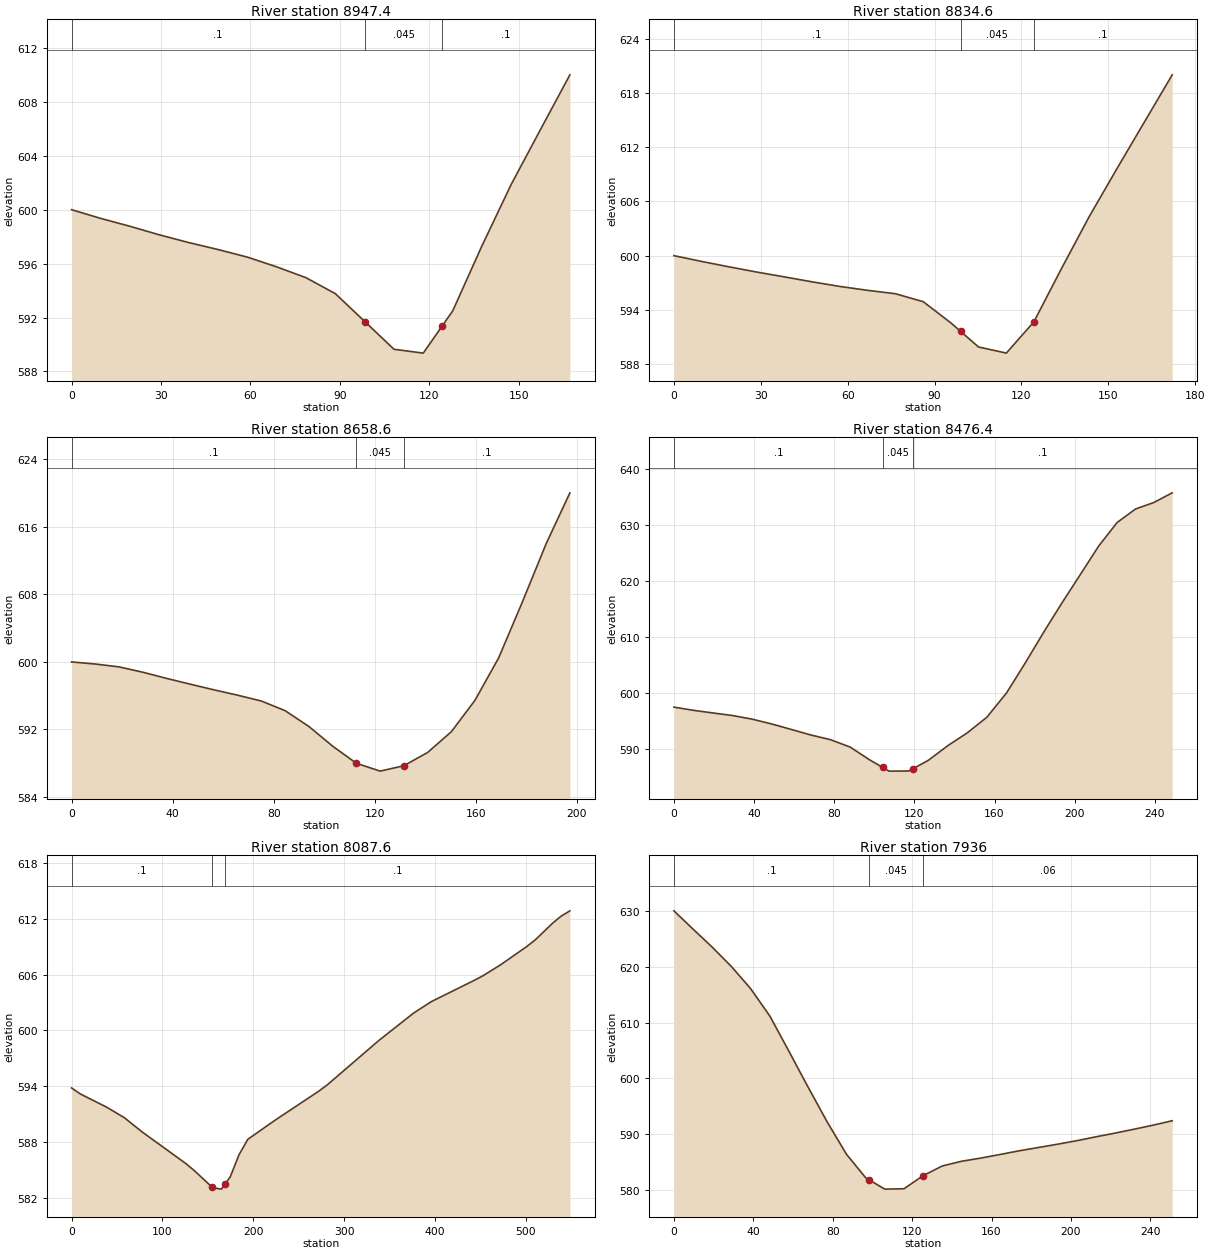
Type RM Length L Ch R = 1 ,8947.4  ,113.8,112.8,111.7
XS GIS Cut Line= 2
     1612489.268      483628.571     1612586.405      483492.476
#Sta/Elev= 20
       0     600     9.8  599.35    19.7  598.76    29.5  598.13    39.3  597.56
    49.2  597.04      59  596.48    68.8  595.76    78.7  594.95    88.5  593.77
    98.4   591.7   108.2  589.64   109.4  589.61     118  589.36   124.4  591.39
   127.9   592.5   137.7  597.32   147.5  601.87   157.4  605.97   167.2     610
#Mann= 3 , 0 , 0
       0      .1       0    98.4    .045       0   124.4      .1       0
Bank Sta=98.4,124.4
XS Rating Curve= 0 ,0
Exp/Cntr=0.3,0.1

Type RM Length L Ch R = 1 ,8834.6  ,172.6,176,179.5
XS GIS Cut Line= 2
     1612592.261      483686.457     1612685.405      483541.688
#Sta/Elev= 21
       0     600     9.6  599.36    19.1  598.76    28.7  598.18    38.2  597.65
    47.8   597.1    57.4  596.59      67  596.16    76.5  595.79    86.1  594.91
    95.6  592.58      99  591.63   105.2   589.9     114  589.28   114.8  589.22
   124.3  592.67   133.9   598.6   143.4   604.3     153  609.62   162.6  614.84
   172.1     620
#Mann= 3 , 0 , 0
       0      .1       0      99    .045       0   124.3      .1       0
Bank Sta=99,124.3
XS Rating Curve= 0 ,0
Exp/Cntr=0.3,0.1

Type RM Length L Ch R = 1 ,8658.6  ,184.8,182.2,179.7
XS GIS Cut Line= 2
     1612700.621      483794.632     1612824.527      483641.199
#Sta/Elev= 24
       0     600     9.4  599.75    18.8  599.41    28.2  598.78    37.6  598.05
      47  597.36    56.4  596.69    65.7  596.06    75.1  595.37    84.5  594.23
    93.9  592.36   103.3  590.03   104.5  589.77   112.7     588   119.5  587.33
   122.1  587.07   131.5  587.71   140.9  589.28   150.3  591.74   159.6  595.44
     169  600.47   178.4   607.1   187.8  613.99   197.2  620.02
#Mann= 3 , 0 , 0
       0      .1       0   112.7    .045       0   131.5      .1       0
Bank Sta=112.7,131.5
XS Rating Curve= 0 ,0
Exp/Cntr=0.3,0.1

Type RM Length L Ch R = 1 ,8476.4  ,363.1,388.8,413.4
XS GIS Cut Line= 3
     1612866.127      483896.901     1612955.038      483756.751
     1612984.617      483679.453
#Sta/Elev= 29
       0  597.46     9.8  596.89    19.5  596.42    29.3  595.96      39  595.32
    48.8  594.46    58.6  593.48    68.3   592.5    78.1  591.66    87.9  590.35
    97.6  588.08   104.2  586.71   107.4  586.05   117.2  586.07   119.2  586.46
   126.9  587.96   136.7  590.59   146.4  592.87   156.2  595.66     166  599.99
   175.2  605.25   184.4  610.73   193.6     616   202.8  621.08     212  626.18
   221.2  630.38   230.4  632.79   239.5  633.94   248.7  635.67
#Mann= 3 , 0 , 0
       0      .1       0   104.2    .045       0   119.2      .1       0
Bank Sta=104.2,119.2
XS Rating Curve= 0 ,0
Exp/Cntr=0.3,0.1

Type RM Length L Ch R = 1 ,8087.6  ,170.8,151.6,132.4
XS GIS Cut Line= 3
     1613056.231      483988.047     1613337.481      483991.953
     1613558.835      483842.214
#Sta/Elev= 28
       0  593.81     9.7  593.16    38.8  591.73    58.2   590.6    77.6  589.08
   126.1  585.65   135.8  584.85   154.2  583.17   155.2  583.08   164.9  582.92
   169.2   583.5   174.6  584.23   184.3  586.62     194  588.28   223.1  590.28
   271.6  593.43   281.3  594.13   338.5  598.94   376.7  601.88   395.8  603.09
   443.5   605.4   453.1   605.9   472.2  607.06   500.8  609.01   510.3  609.74
   529.4  611.53     539  612.31   548.5  612.87
#Mann= 3 , 0 , 0
       0      .1       0   154.2    .045       0   169.2      .1       0
Bank Sta=154.2,169.2
XS Rating Curve= 0 ,0
Exp/Cntr=0.3,0.1

Type RM Length L Ch R = 1 ,7936    ,365.6,355.1,344.2
XS GIS Cut Line= 2
     1613156.455      484204.939     1613330.971      484024.505
#Sta/Elev= 29
       0     630     9.6  626.74    19.3   623.5      29  620.02    38.6  616.09
    48.3  611.18    57.9  604.89    67.6  598.44    77.2  592.22    86.9  586.44
    96.6  582.22    98.1   581.9   106.2  580.19   113.1  580.24   115.9  580.26
   125.5  582.59   135.2  584.34   144.8  585.17   154.5  585.74   164.1  586.38
   173.8  587.04   183.4  587.63   193.1  588.22   202.8  588.85   212.4  589.54
   222.1  590.21   231.7  590.91   241.4  591.64     251  592.43
#Mann= 3 , 0 , 0
       0      .1       0    98.1    .045       0   125.5     .06       0
Bank Sta=98.1,125.5
XS Rating Curve= 0 ,0
Exp/Cntr=0.3,0.1

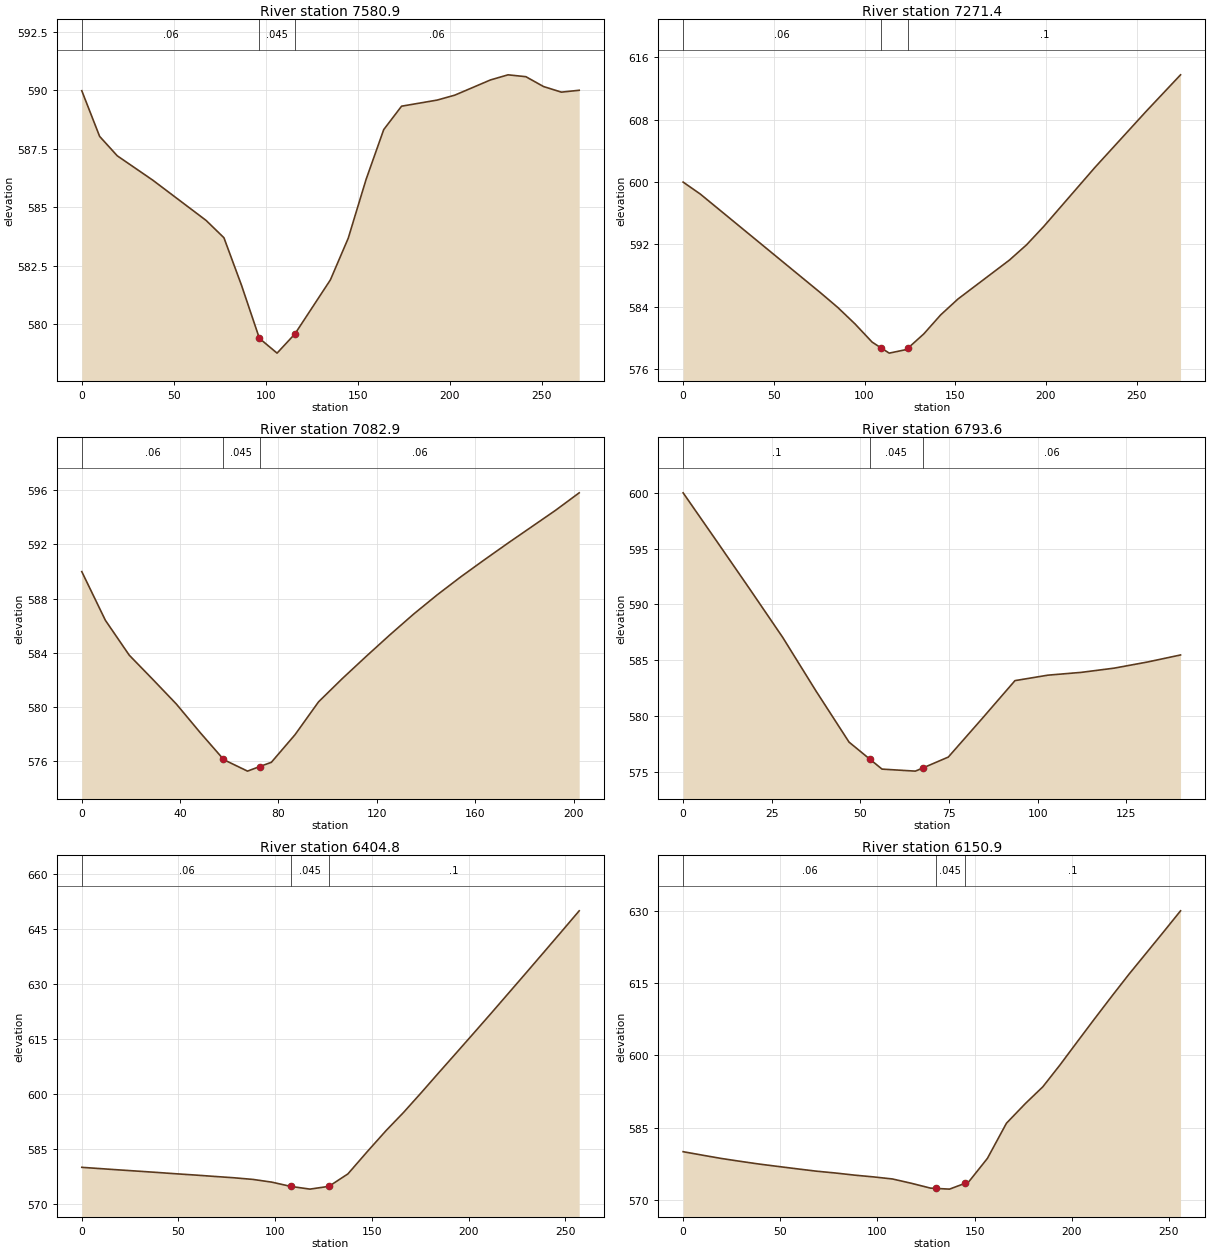
Type RM Length L Ch R = 1 ,7580.9  ,287.9,309.4,330.9
XS GIS Cut Line= 2
     1613479.716      484413.173       1613563.8      484156.117
#Sta/Elev= 23
       0  589.98     9.7  588.03    19.3   587.2    38.6  586.16    67.6  584.44
    77.3   583.7    86.9  581.66    96.6   579.4   106.2  578.77   115.9  579.59
   135.2   581.9   144.9  583.68   154.6  586.19   164.2  588.32   173.9  589.32
   193.2  589.58   202.8  589.79   222.2  590.44   231.8  590.66   241.5  590.58
   251.1  590.16   260.8  589.92   270.5     590
#Mann= 3 , 0 , 0
       0     .06       0    96.6    .045       0   115.9     .06       0
Bank Sta=96.6,115.9
XS Rating Curve= 0 ,0
Exp/Cntr=0.3,0.1

Type RM Length L Ch R = 1 ,7271.4  ,189,188.5,187.9
XS GIS Cut Line= 3
     1613573.643      484581.495     1613744.749      484525.938
     1613837.481       484508.88
#Sta/Elev= 19
       0     600     9.5  598.46    75.8  585.79    85.2  583.93    94.7  581.82
   104.2  579.47     109  578.75   113.6  578.06   123.1  578.52     124  578.71
   132.6  580.51     142  582.97   151.5     585   179.9     590   189.3  591.95
   198.8  594.31     227  601.88   255.3  609.09   274.2  613.76
#Mann= 3 , 0 , 0
       0     .06       0     109    .045       0     124      .1       0
Bank Sta=109,124
XS Rating Curve= 0 ,0
Exp/Cntr=0.3,0.1

Type RM Length L Ch R = 1 ,7082.9  ,288.6,289.3,290
XS GIS Cut Line= 2
     1613662.225      484742.505     1613853.106      484675.547
#Sta/Elev= 24
       0     590     9.6  586.41    19.3  583.84    28.9  582.05    38.5  580.23
    48.2  578.12    57.4  576.21    57.8  576.13    67.4  575.29    72.4  575.63
    77.1  575.94    86.7  577.97    96.3   580.4     106  582.12   115.6  583.74
   125.2  585.32   134.9  586.86   144.5  588.28   154.1  589.61   163.8  590.88
   173.4  592.11     183  593.31   192.6  594.51   202.3  595.81
#Mann= 3 , 0 , 0
       0     .06       0    57.4    .045       0    72.4     .06       0
Bank Sta=57.4,72.4
XS Rating Curve= 0 ,0
Exp/Cntr=0.3,0.1

Type RM Length L Ch R = 1 ,6793.6  ,379.6,388.8,398
XS GIS Cut Line= 2
     1613741.501      485017.528     1613875.242      484975.026
#Sta/Elev= 18
       0     600     9.4   595.7    18.7  591.42    28.1  587.04    37.4  582.28
    46.8  577.66    52.6  576.15    56.1  575.24    65.5  575.06    67.6  575.34
    74.8  576.32    84.2  579.72    93.6  583.17   102.9  583.66   112.3  583.91
   121.6  584.29     131  584.84   140.3  585.47
#Mann= 3 , 0 , 0
       0      .1       0    52.6    .045       0    67.6     .06       0
Bank Sta=52.6,67.6
XS Rating Curve= 0 ,0
Exp/Cntr=0.3,0.1

Type RM Length L Ch R = 1 ,6404.8  ,245.5,254,262.2
XS GIS Cut Line= 3
     1613735.136      485366.564      1613891.65      485382.236
      1613980.21      485428.424
#Sta/Elev= 30
       0     580     9.8  579.64    19.7  579.28    29.5  578.94    39.3  578.59
    49.2  578.22      59  577.88    68.8  577.51    78.6  577.15    88.5   576.7
    98.3  575.95   108.1  574.79     118  574.05   119.5  574.17   127.8  574.81
   134.5  577.13   137.6   578.2   147.5  584.21   157.3     590   166.4  594.99
   175.5  600.35   184.5  605.77   193.6  611.19   202.7  616.64   211.8  622.12
   220.9  627.67   229.9  633.16     239  638.75   248.1  644.36   257.2     650
#Mann= 3 , 0 , 0
       0     .06       0   108.1    .045       0   127.8      .1       0
Bank Sta=108.1,127.8
XS Rating Curve= 0 ,0
Exp/Cntr=0.3,0.1

Type RM Length L Ch R = 1 ,6150.9  ,254.7,239.9,224
XS GIS Cut Line= 3
     1613623.079      485539.716     1613781.144      485617.647
     1613856.091      485644.999
#Sta/Elev= 30
       0     580     9.8  579.29    19.6   578.6    29.4     578    39.2  577.43
      49  576.93    58.7  576.44    68.5  575.96    78.3  575.58    88.1  575.14
    97.9  574.77   107.7  574.34   117.5  573.44   127.3  572.44     130  572.38
   137.1  572.23     145  573.42   146.9   573.7   156.6  578.61   166.4  585.91
   176.2  590.02   185.1  593.46     194  598.03   202.8  602.79   211.7  607.56
   220.6  612.26   229.4  616.81   238.3   621.2   247.2   625.6     256     630
#Mann= 3 , 0 , 0
       0     .06       0     130    .045       0     145      .1       0
Bank Sta=130,145
XS Rating Curve= 0 ,0
Exp/Cntr=0.3,0.1

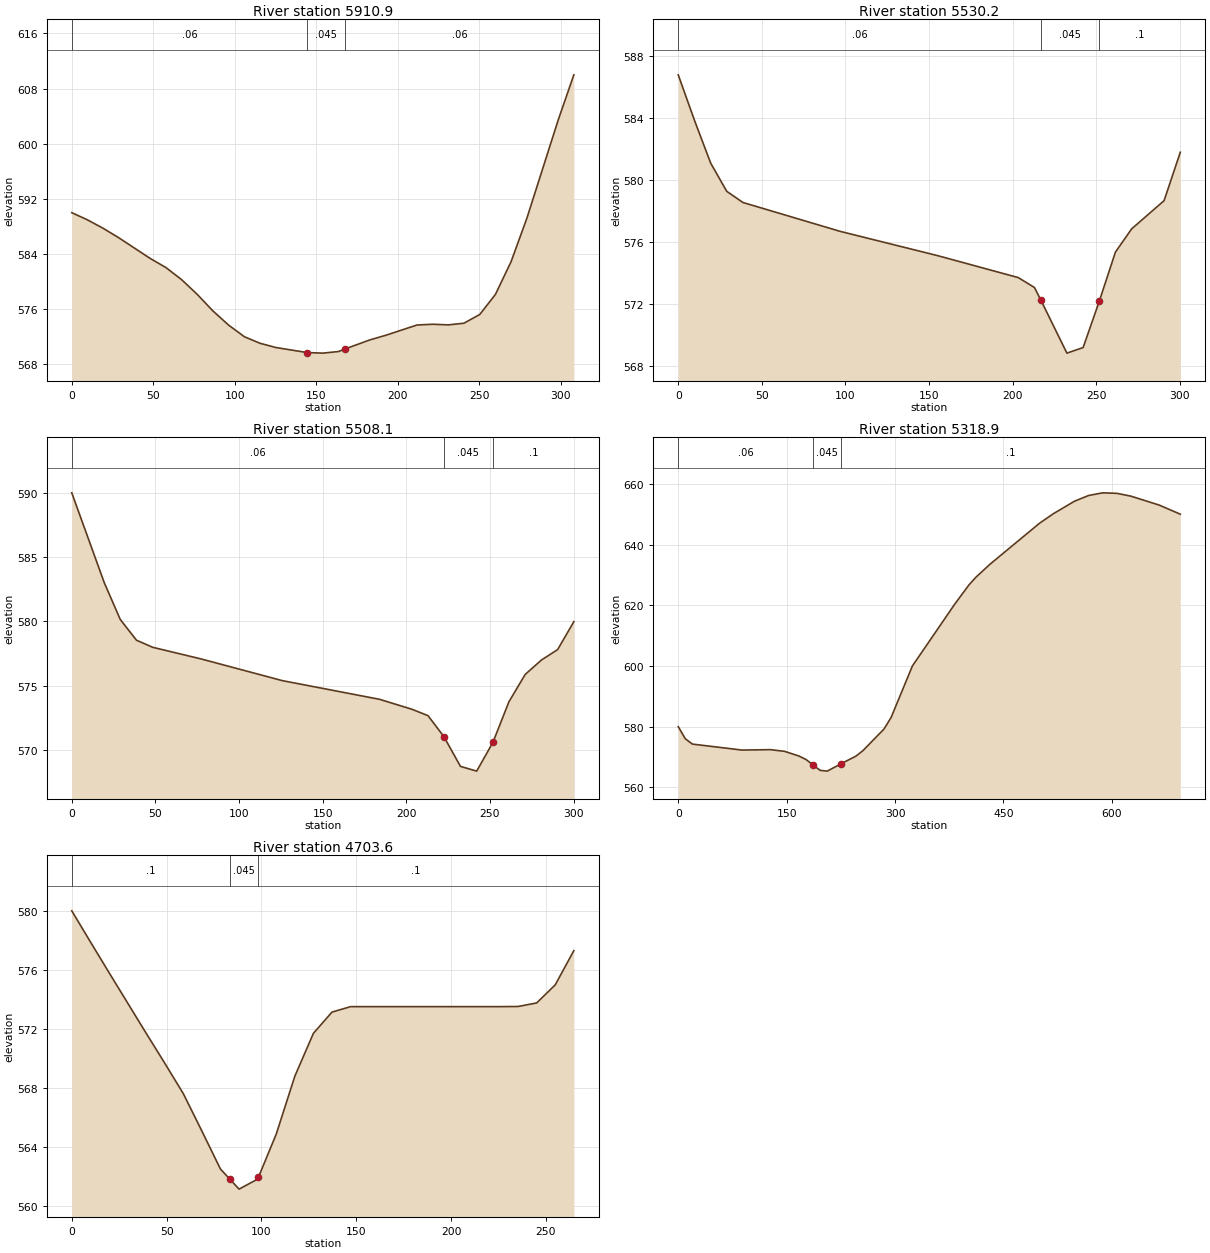
Type RM Length L Ch R = 1 ,5910.9  ,373.7,380.7,388.2
XS GIS Cut Line= 2
     1613489.341      485844.833     1613792.951      485792.849
#Sta/Elev= 29
       0     590     9.6  588.96    19.2  587.74    28.9  586.35    48.1  583.36
    57.8  582.03    67.4  580.28      77  578.14    86.6  575.74    96.3  573.67
   105.9     572   115.5  571.05   125.1  570.44   144.4   569.7     154  569.62
   163.6  569.85   167.8  570.24   182.9  571.54   192.5   572.2   211.8   573.7
   221.4  573.81     231  573.72   240.6  573.96   250.3  575.23   259.9  578.14
   269.5  582.89   279.2   589.2   298.4  603.44     308     610
#Mann= 3 , 0 , 0
       0     .06       0   144.4    .045       0   167.8     .06       0
Bank Sta=144.4,167.8
XS Rating Curve= 0 ,0
Exp/Cntr=0.3,0.1

Type RM Length L Ch R = 1 ,5530.2  ,22,22.1,22
XS GIS Cut Line= 2
     1613529.578      486114.345     1613829.707      486109.491
#Sta/Elev= 17
       0   586.8     9.7  583.87    19.4  581.11      29  579.29    38.7  578.57
    96.8  576.71   154.9  575.15   203.3  573.73     213  573.09   216.8  572.28
   232.4  568.86   242.1  569.22   251.8  572.22   261.4  575.37   271.1  576.87
   290.5  578.69   300.2  581.81
#Mann= 3 , 0 , 0
       0     .06       0   216.8    .045       0   251.8      .1       0
Bank Sta=216.8,251.8
XS Rating Curve= 0 ,0
Exp/Cntr=0.3,0.1

Type RM Length L Ch R = 1 ,5508.1  ,189.8,189.3,188.5
XS GIS Cut Line= 2
     1613528.493      486136.046     1613828.622      486131.192
#Sta/Elev= 19
       0  589.99    19.4  583.02      29  580.15    38.7  578.54    48.4  577.99
    77.5  577.08   125.9   575.4     184  573.95   203.3  573.18     213  572.68
   222.5  571.05   232.4  568.74   242.1  568.37   251.8   570.6   261.4  573.76
   271.1  575.88   280.8     577   290.5  577.81   300.2  579.98
#Mann= 3 , 0 , 0
       0     .06       0   222.5    .045       0   251.8      .1       0
Bank Sta=222.5,251.8
XS Rating Curve= 0 ,0
Exp/Cntr=0.3,0.1

Type RM Length L Ch R = 1 ,5318.9  ,600.3,615.2,628.7
XS GIS Cut Line= 3
     1613574.672      486328.145     1613898.445      486314.091
      1614154.35      486582.369
#Sta/Elev= 30
       0  579.99     9.8  575.98    19.6  574.23    88.4  572.26   127.7   572.4
   147.3  571.83     167   570.3   176.8  569.16   186.6  567.35   196.4  565.57
   206.2  565.32   225.9  567.83   245.5   570.2   255.3  572.01   284.8   579.2
   294.6  583.01   324.1     600   382.6  620.34   402.1  626.62   411.9  629.22
   431.4   633.5   499.7  646.96   519.2  650.17   548.5  654.29     568  656.17
   587.5  657.04     607  656.87   626.5  655.94   665.6     653   694.8     650
#Mann= 3 , 0 , 0
       0     .06       0   186.6    .045       0   225.9      .1       0
Bank Sta=186.6,225.9
XS Rating Curve= 0 ,0
Exp/Cntr=0.3,0.1

Type RM Length L Ch R = 1 ,4703.6  ,4702.3,4703.6,4696.3
XS GIS Cut Line= 2
     1613373.527      486609.283     1613602.093      486742.767
#Sta/Elev= 30
       0     580     9.8   577.9    19.6  575.82    29.4  573.76    39.2   571.7
      49  569.67    58.8   567.6    68.6  565.06    78.4  562.48    83.4  561.79
    88.2  561.12      98   561.8    98.4  561.92   107.8  564.85   117.6  568.78
   127.4  571.69   137.2  573.13     147   573.5   156.8   573.5   166.7   573.5
   176.5   573.5   186.3   573.5   196.1   573.5   205.9   573.5   215.7   573.5
   225.5   573.5   235.3  573.51   245.1  573.75   254.9  574.98   264.7   577.3
#Mann= 3 , 0 , 0
       0      .1       0    83.4    .045       0    98.4      .1       0
Bank Sta=83.4,98.4
XS Rating Curve= 0 ,0
Exp/Cntr=0.3,0.1

Chan Stop Cuts=-1
Use User Specified Reach Order=0
Composite Channel Slope=5